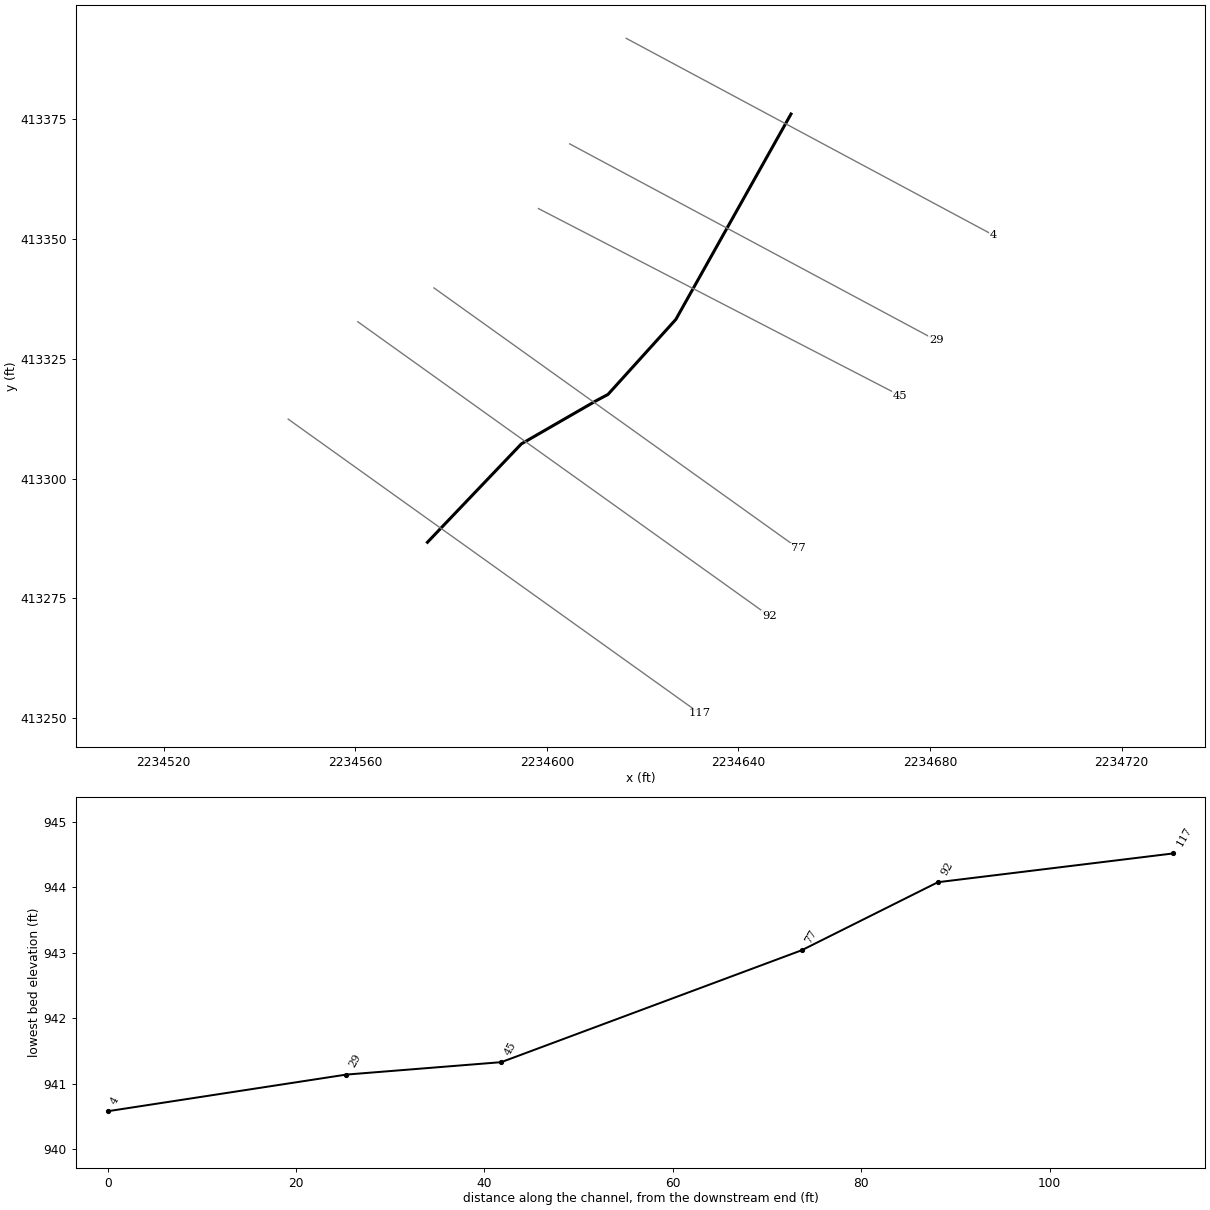
--- 118689.prj (project) ---

Proj Title=STA-SSV 011-Bridge
Current Plan=p03
Default Exp/Contr=0.3,0.1
English Units
Geom File=g01
Geom File=g02
Flow File=f01
Plan File=p01
Plan File=p03
Y Axis Title=Elevation
X Axis Title(PF)=Main Channel Distance
X Axis Title(XS)=Station
BEGIN DESCRIPTION:
END DESCRIPTION:
DSS Export Rating Curves= 0
DSS Export Rating Curve Sorted= 0
DSS Export Volume Flow Curves= 0
DXF Filename=new.
DXF OffsetX= 0
DXF OffsetY= 0
DXF ScaleX= 1
DXF ScaleY= 10

--- 118689.p03 (plan) ---

Plan Title=proposed
Program Version=6.30
Short Identifier=prop
Geom File=g02
Flow File=f01
Subcritical Flow
K Sum by GR= 0
Std Step Tol= 0.01
Critical Tol= 0.01
Num of Std Step Trials= 20
Max Error Tol= 0.3
Flow Tol Ratio= 0.001
Split Flow NTrial= 30
Split Flow Tol= 0.02
Split Flow Ratio= 0.02
Log Output Level= 0
Friction Slope Method= 1
Unsteady Friction Slope Method= 2
Unsteady Bridges Friction Slope Method= 1
Parabolic Critical Depth
Global Vel Dist= 0 , 0 , 0
Global Log Level= 0
CheckData=True
Encroach Param=-1 ,0,0, 0
Computation Interval=1MIN
Output Interval=1HOUR
Instantaneous Interval=1HOUR
Mapping Interval=1HOUR
Computation Time Step Use Courant=        0
Computation Time Step Use Time Series=    0
Computation Time Step Count To Double=0
Computation Time Step Max Doubling=0
Computation Time Step Max Halving=0
Computation Time Step Residence Courant=0
Run HTab= 0
Run UNet= 0
Run Sediment= 0
Run PostProcess= 0
Run WQNet= 0
Run RASMapper= 0
UNET Theta= 1
UNET Theta Warmup= 1
UNET ZTol= 0.02
UNET ZSATol= 0.02
UNET MxIter= 20
UNET Max Iter WO Improvement= 0
UNET MaxInSteps= 0
UNET DtIC= 0
UNET DtMin= 0
UNET MaxCRTS= 20
UNET WFStab= 2
UNET SFStab= 1
UNET WFX= 1
UNET SFX= 1
UNET Gravity=32.17405
UNET 1D Methodology=Finite Difference
UNET DSS MLevel= 4
UNET Pardiso=0
UNET DZMax Abort= 100
UNET Use Existing IB Tables=-1
UNET Froude Reduction=False
UNET Froude Limit= 0.8
UNET Froude Power= 4
UNET D1 Cores= 0
UNET WindReference=Eulerian
UNET WindDragFormulation=Hsu (1988)
UNET D2 Coriolis=0
UNET D2 Cores= 0
UNET D2 Theta= 1
UNET D2 Theta Warmup= 1
UNET D2 Z Tol= 0.01
UNET D2 Volume Tol= 0.01
UNET D2 Max Iterations= 20
UNET D2 Equation= 0
UNET D2 RampUpFraction=0.1
UNET D2 TimeSlices= 1
UNET D2 Turbulence Formulation=None
UNET D2 Eddy Viscosity=0.3
UNET D2 Transverse Eddy Viscosity=0.1
UNET D2 Smagorinsky Mixing=0.05
UNET D2 BCVolumeCheck=0
UNET D2 Cores=0
UNET D2 SolverType=PARDISO (Direct)
UNET D2 Minimum Iterations= 3
UNET D2 Maximum Iterations= 30
UNET D2 Restart Number= 10
UNET D2 Relaxation Coeff=1.3
UNET D2 SOR Precondition Iterations= 10
UNET D2 ILUT Maximum Fill= 8
UNET D2 ILUT Tolerance=1E-08
UNET D2 Convergence Tolerance=0.00001
UNET D1D2 MaxIter= 0
UNET D1D2 ZTol=0.01
UNET D1D2 QTol=0.1
UNET D1D2 MinQTol=1
Write IC File= 0
Write IC File at Fixed DateTime=0
Write IC File at Sim End=0
Echo Input=False
Echo Parameters=False
Echo Output=False
Write Detailed= 0
HDF Write Warmup=0
HDF Write Time Slices=0
HDF Flush=0
HDF Compression= 1
HDF Chunk Size= 1
HDF Spatial Parts= 1
HDF Use Max Rows=0
HDF Fixed Rows= 1
Calibration Method= 0
Calibration Iterations= 20
Calibration Max Change=0.05
Calibration Tolerance=0.2
Calibration Maximum=1.5
Calibration Minimum=0.5
Calibration Optimization Method= 1
WQ AD Non Conservative
WQ ULTIMATE=-1
WQ Max Comp Step=1HOUR
WQ Output Interval=15MIN
WQ Output Selected Increments= 0
WQ Output face flow=0
WQ Output face velocity=0
WQ Output face area=0
WQ Output face dispersion=0
WQ Output cell volume=0
WQ Output cell surface area=0
WQ Output cell continuity=0
WQ Output cumulative cell continuity=0
WQ Output face conc=0
WQ Output face dconc_dx=0
WQ Output face courant=0
WQ Output face peclet=0
WQ Output face adv mass=0
WQ Output face disp mass=0
WQ Output cell mass=0
WQ Output cell source sink temp=0
WQ Output nsm pathways=0
WQ Output nsm derived pathways=0
WQ Create Restart=0
WQ Fixed Restart=0
WQ System Summary=0
WQ Write To DSS=0
Sorting and Armoring Iterations= 10
XS Update Threshold= 0.02
Bed Roughness Predictor= 0
Hydraulics Update Threshold= 0.02
Energy Slope Method= 1
Volume Change Method= 1
Sediment Retention Method= 0
Sediment TS Multiplier= 1
Warm Up Method= 0
XS Weighting Method= 0
Number of US Weighted Cross Sections= 1
Number of DS Weighted Cross Sections= 1
Upstream XS Weight=0
Main XS Weight=1
Downstream XS Weight=0
Number of DS XS's Weighted with US Boundary= 1
Upstream Boundary Weight= 1
Weight of XSs Associated with US Boundary= 0
Number of US XS's Weighted with DS Boundary= 1
Downstream Boundary Weight= 0.5
Weight of XSs Associated with DS Boundary= 0.5
Percentile Method= 0
Sediment Output Level= 3
Mass or Volume Output= 0
Output Increment Type= 1
Profile and TS Output Increment= 1
Transport Output Increment 1
XS Output Flag= 0
XS Output Increment= 10
Read HDF5 Sediment Hotstart= 0
Sediment Hotstart Type= 0
Write Gradation File= 0
Read Gradation Hotstart= 0
Write HDF5 File= 1
Write Binary Output= 1
Write DSS Sediment File= 0
DSS Sediment Output Type= 1
SV Curve= 0
Specific Gage Flag= 0
Subcell Erosion Methods= 0
Subcell Deposition Methods= 0
Advection Scheme= 1
Matrix Solver= 0
Implicit Weighting Factor= 1
Maximum Outer Loop Convergence Iterations= 5
Convergence Maximum Absolute= 0.001
Convergence RMSE= 0.0001
Grain Fractions Max Abs Error= 0.001
Max Subgrid Regions= 1
Max Subgrid Length Scale= 3.402823E+38
Initial Layer Thickness= 3.402823E+38
Min Layer Thickness= 3.402823E+38
Max Layer Thickness= 3.402823E+38
Number of Layers= 5

--- 118689.p01 (plan) ---

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Plan Title=existing
Program Version=5.05
Short Identifier=exist
Geom File=g01
Flow File=f01
HDF Face Node Velocities=0
WQ Output MaxMinRange=-1
WQ Daily Max Min Mean=-1
WQ Daily Range=0
WQ Daily Time=0
WQ Use Fixed Temperature=0

--- 118689.f01 (steady flow) ---

Flow Title=flow
Program Version=5.05
Number of Profiles= 4
Profile Names=Q4%,Q1%,Q20%,Q10%
River Rch & RM=river,Reach           ,117
     235     341     127     172
Boundary for River Rch & Prof#=river,Reach           , 1
Up Type= 3
Up Slope=0.02
Dn Type= 3
Dn Slope=0.02
Boundary for River Rch & Prof#=river,Reach           , 2
Up Type= 3
Up Slope=0.02
Dn Type= 3
Dn Slope=0.02
DSS Import GetInterval= 0
DSS Import GetPeak= 0
DSS Import FillOption= 0

--- 118689.g02 (geometry) ---

Geom Title=proposed
Program Version=6.30

River Reach=river           ,Reach
Reach XY= 7
 2234575.0559577  413286.7089445 2234594.6679999  413307.2570104
 2234594.6679999  413307.2570104 2234610.4629999  413316.3630104
 2234612.7609999  413317.5870104 2234626.9232604  413333.2420801
 2234650.9782927  413376.1443551

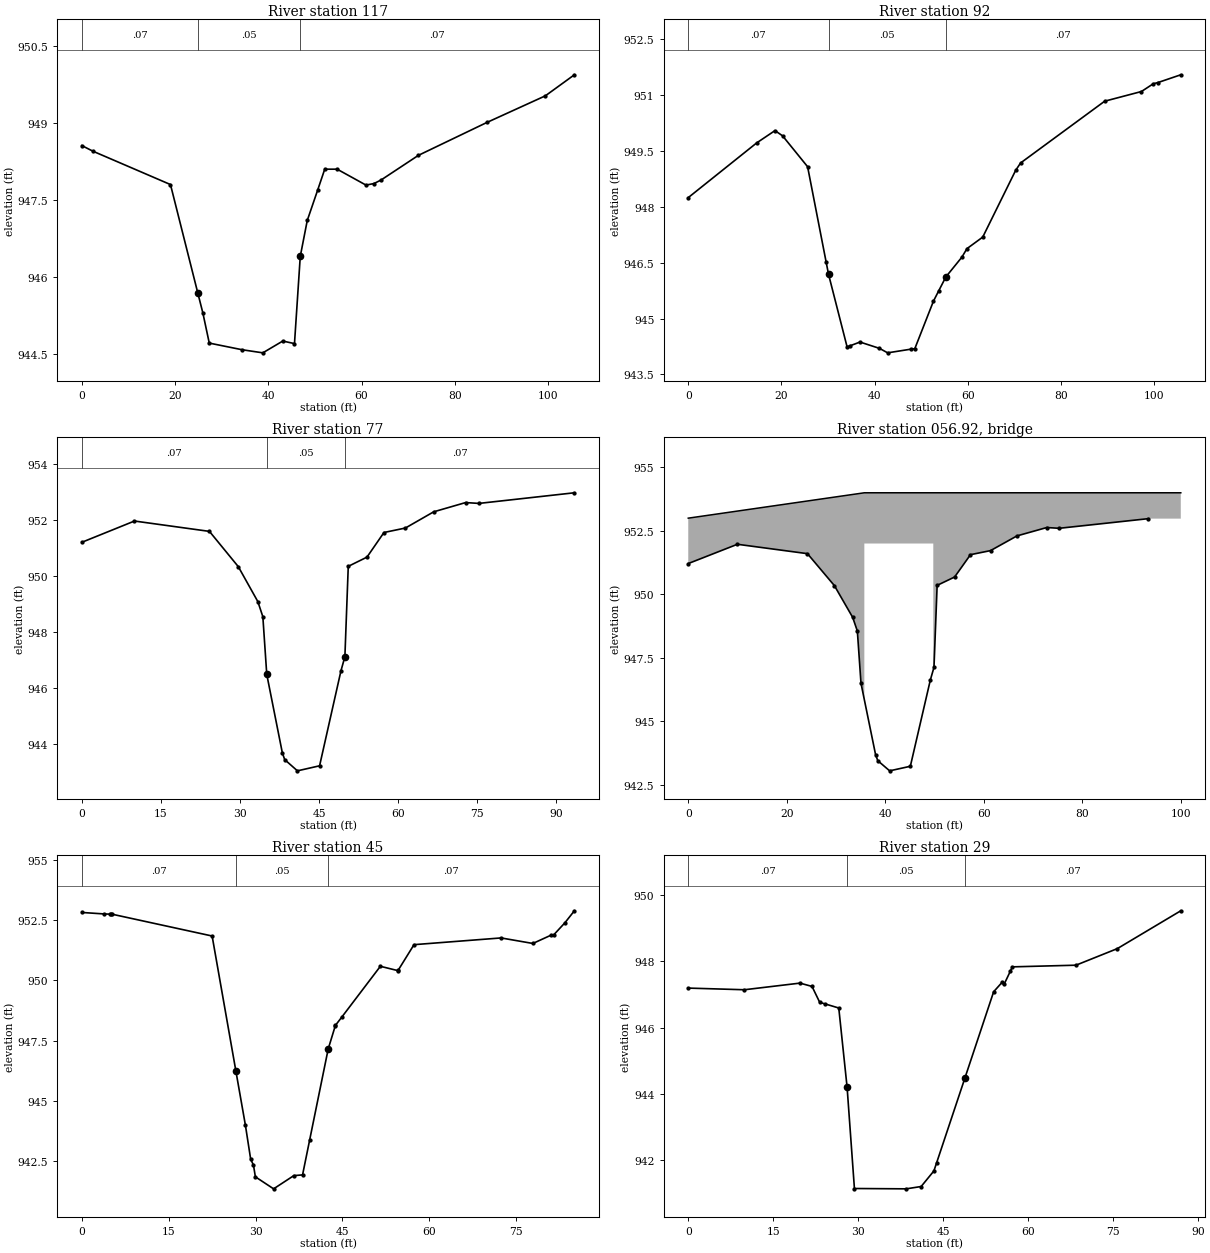
Type RM Length L Ch R = 1 ,117     ,25.01,25,25.54
XS GIS Cut Line= 2
2234545.97385707 413312.424258542234631.91369281 413250.97833176
#Sta/Elev= 22
       0  948.562.380005  948.45   19.01   947.8   24.86  945.69   25.95   945.3
   27.33  944.71    34.4  944.58   38.82  944.52    43.1  944.75   45.61   944.7
   46.85   946.4   48.35   947.1   50.61   947.7    52.1   948.1   54.76   948.1
   60.94  947.79   62.67  947.82    64.2  947.89    72.2  948.37   86.87  949.01
   99.43  949.53  105.65  949.94
#Mann= 3 ,0,0
       0     .07       0   24.86     .05       0   46.85     .07       0
Bank Sta=24.86,46.85
XS Rating Curve= 0 ,0
Exp/Cntr=0.3,0.1

Type RM Length L Ch R = 1 ,92      ,14.99,14.46,14.92
XS GIS Cut Line= 2
2234560.51426357 413332.76084082 2234646.4540993 413271.31491404
#Sta/Elev= 27
       0  948.25   14.68  949.72    18.6  950.05   20.23  949.91    25.6  949.08
   29.59  946.51   30.09  946.19   34.07  944.24   34.72  944.27   36.84  944.37
   41.02   944.2   42.77  944.08   47.82  944.18   48.59  944.19    52.6  945.47
   53.74  945.75   55.26  946.12   58.69  946.65   59.79  946.88   63.17  947.19
   70.22  948.98   71.28  949.18   89.32  950.84    97.2   951.1   99.77  951.31
  100.72  951.34  105.65  951.55
#Mann= 3 ,0,0
       0     .07       0   30.09     .05       0   55.26     .07       0
Bank Sta=30.09,55.26
XS Rating Curve= 0 ,0
Exp/Cntr=0.3,0.1

Type RM Length L Ch R = 1 ,77      ,34.46,31.89,34.46
XS GIS Cut Line= 2
2234576.42379955 413339.82539463  2234652.419035 413285.48973487
#Sta/Elev= 21
       0  951.219.979996  951.97    24.2   951.6   29.67  950.34   33.38  949.09
   34.33  948.55   35.07  946.49   38.03  943.68   38.48  943.44   40.89  943.04
   45.09  943.22   49.15  946.62   49.89  947.12   50.53  950.35   54.08  950.68
    57.3  951.56   61.37  951.72   66.74   952.3   72.79  952.63   75.31   952.6
   93.42  952.98
#Mann= 3 ,0,0
       0     .07       0   35.07     .05       0   49.89     .07       0
Bank Sta=35.07,49.89
XS Rating Curve= 0 ,0
Exp/Cntr=0.3,0.1

Type RM Length L Ch R = 3 ,056.92  ,,,
Bridge Culvert--1,0,-1,-1, 0
Deck Dist Width WeirC Skew NumUp NumDn MinLoCord MaxHiCord MaxSubmerge Is_Ogee
7.4,16,2.6,0, 11, 11, , , 0.98, 0, 0,0,,
       0   35.75   35.75   49.75   49.75      60      65      68      75      80
     100
     953     954     954     954     954     954     954     954     954     954
     954
       0       0     952     952     946     946
        
       0   27.75   27.75   41.75   41.75      60      65      68      75      80
      93
     953     954     954     954     954     954     954     954     954     954
     954
       0       0     952     952     946     946
        
BR Coef=-1 , 0 , 0 ,, 0 ,,,0.8,-1,,0,
WSPro=,,,, 1 ,,,, 0 ,,,, 0 ,,,,-1 ,-1 ,-1 , 0 , 0 , 0 , 0 , 0
BC Design=,, 0 ,, 0 ,,,,,,
BC Use User HTab Curves=0
BC User HTab FreeFlow(D)= 0

Type RM Length L Ch R = 1 ,45      ,16.14,16.45,22.02
XS GIS Cut Line= 2
2234598.24487394  413356.39554292234673.80880896 413317.31074898
#Sta/Elev= 29
       0  952.83    3.75  952.774.809998  952.765.120003  952.755.169998  952.76
    22.5  951.85   26.59  946.25   28.24  943.99   29.16  942.56   29.64  942.32
   29.97  941.83   33.12  941.33   36.61  941.88   38.12  941.91   39.36  943.38
   42.55  947.15   43.78  948.12   43.79  948.13   44.91  948.48   51.56  950.59
   54.58  950.41   54.62  950.42   57.37  951.49   72.41  951.77    77.9  951.54
   80.99  951.88   81.47  951.89   83.43   952.4   85.07   952.9
#Mann= 3 ,0,0
       0     .07       0   26.59     .05       0   42.55     .07       0
Bank Sta=26.59,42.55
XS Rating Curve= 0 ,0
Exp/Cntr=0.3,0.1

Type RM Length L Ch R = 1 ,29      ,25.25,25.33,25.49
XS GIS Cut Line= 2
2234604.75877091 413369.914038662234681.33199988 413328.87501039
#Sta/Elev= 22
       0  947.199.899994  947.14   19.71  947.3421.82999  947.24   23.19  946.76
    24.2  946.71   26.55  946.59   28.02   944.2   29.31  941.15   38.45  941.14
   41.08  941.21   43.33  941.68   43.82  941.93   48.82  944.49   53.87  947.08
   55.39  947.37    55.7   947.3   56.82 947.701   57.18  947.83   68.39  947.88
75.68999  948.38   86.88  949.52
#Mann= 3 ,0,0
       0     .07       0   28.02     .05       0   48.82     .07       0
Bank Sta=28.02,48.82
XS Rating Curve= 0 ,0
Exp/Cntr=0.3,0.1

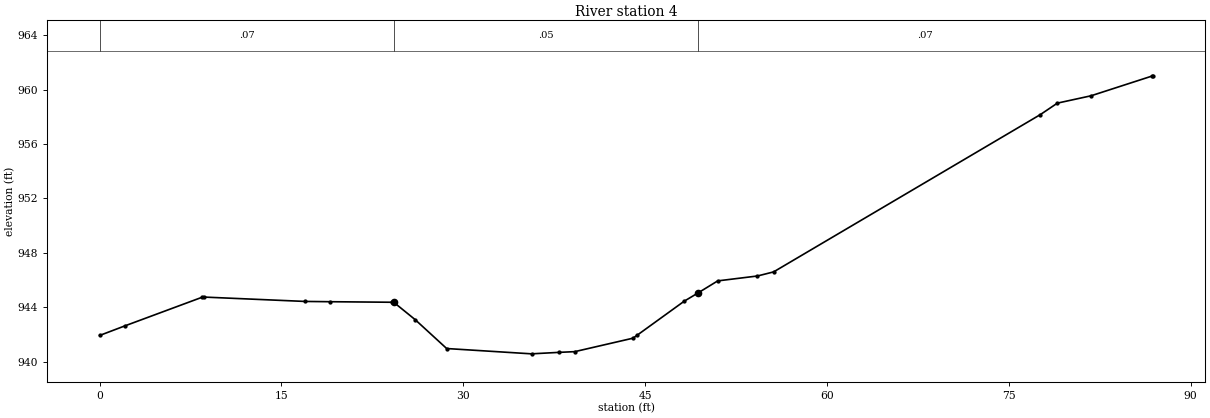
Type RM Length L Ch R = 1 ,4       ,25.54,25,25.01
XS GIS Cut Line= 2
2234616.56825371 413391.948922742234693.14148268 413350.90989447
#Sta/Elev= 25
       0  941.932.099998  942.648.459999  944.748.629997  944.75   16.95  944.43
      19  944.41   24.11  944.37   24.26  944.37   26.02   943.1   28.63  940.97
   35.63  940.58   37.93  940.69   39.19  940.74      44  941.73   44.33  941.94
   48.23  944.45   49.34  945.04   50.99  945.94   54.27   946.3    55.6   946.6
   77.61  958.1679.00999     95981.78999  959.54   86.82  960.99   86.88  961.01
#Mann= 3 ,0,0
       0     .07       0   24.26     .05       0   49.34     .07       0
Bank Sta=24.26,49.34
XS Rating Curve= 0 ,0
Exp/Cntr=0.3,0.1
LCMann Table=0

Chan Stop Cuts=-1
Use User Specified Reach Order=0
Composite Channel Slope=5

--- 118689.g01 (geometry) ---

Geom Title=Existing
Program Version=5.05

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
River Reach=river           ,Reach

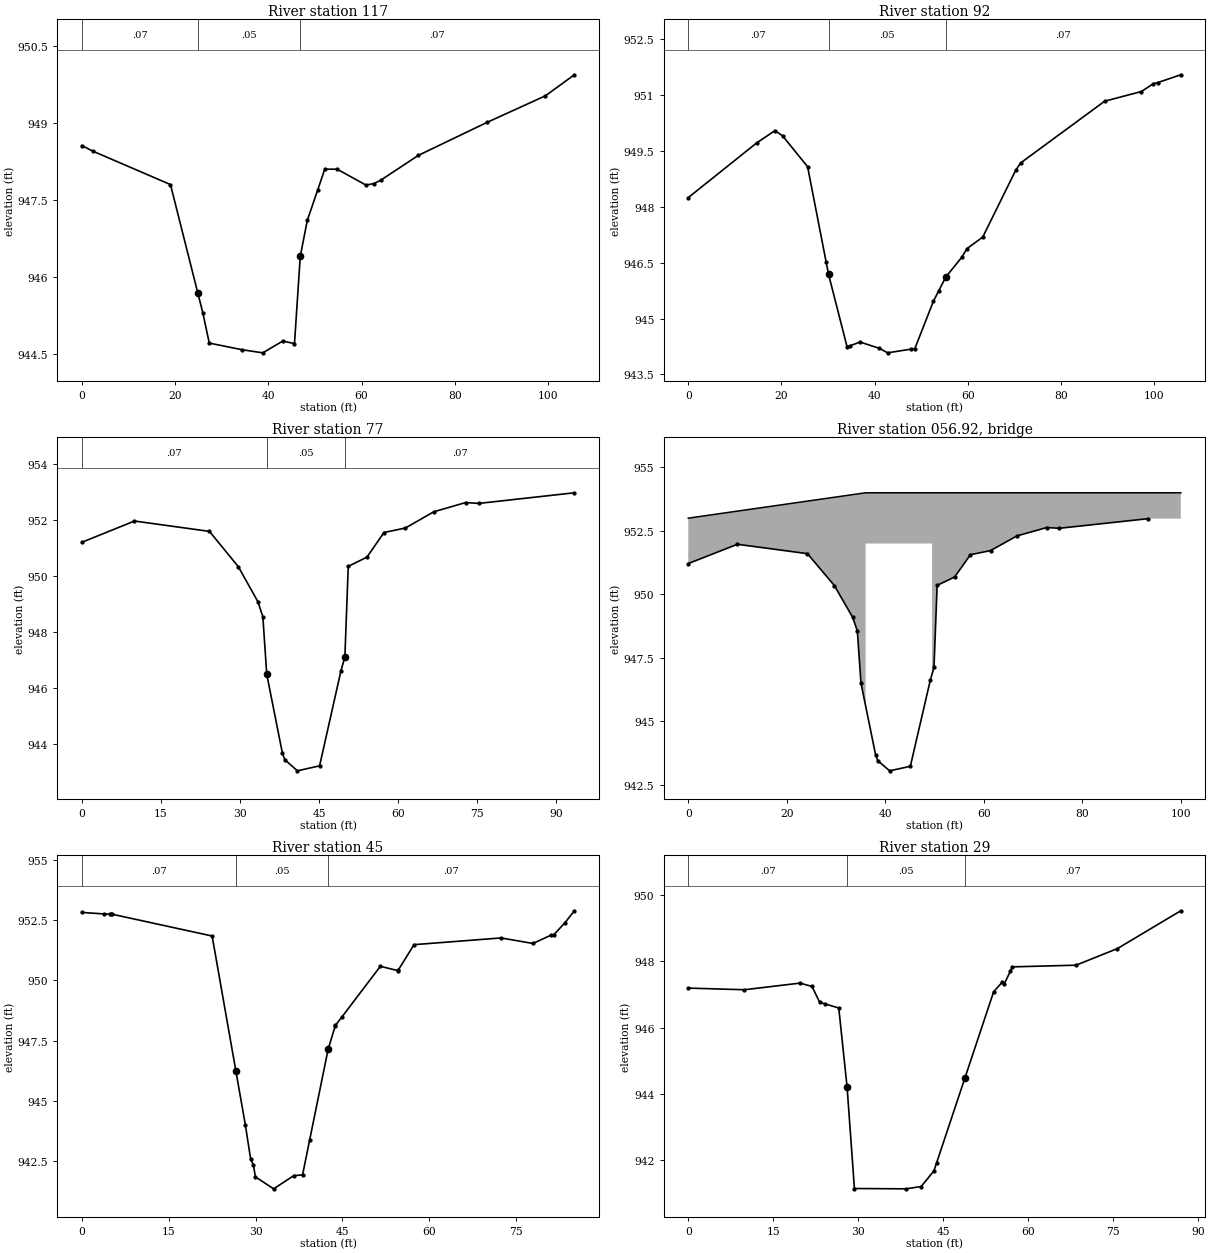
Type RM Length L Ch R = 1 ,117     ,25.01,25,25.54
XS GIS Cut Line= 2
2234545.97385707 413312.424258542234631.91369281 413250.97833176
#Sta/Elev= 22
       0  948.562.380005  948.45   19.01   947.8   24.86  945.69   25.95   945.3
   27.33  944.71    34.4  944.58   38.82  944.52    43.1  944.75   45.61   944.7
   46.85   946.4   48.35   947.1   50.61   947.7    52.1   948.1   54.76   948.1
   60.94  947.79   62.67  947.82    64.2  947.89    72.2  948.37   86.87  949.01
   99.43  949.53  105.65  949.94
#Mann= 3 , 0 , 0
       0     .07       0   24.86     .05       0   46.85     .07       0
Bank Sta=24.86,46.85
XS Rating Curve= 0 ,0
Exp/Cntr=0.3,0.1

Type RM Length L Ch R = 1 ,92      ,14.99,14.46,14.92
XS GIS Cut Line= 2
2234560.51426357 413332.76084082 2234646.4540993 413271.31491404
#Sta/Elev= 27
       0  948.25   14.68  949.72    18.6  950.05   20.23  949.91    25.6  949.08
   29.59  946.51   30.09  946.19   34.07  944.24   34.72  944.27   36.84  944.37
   41.02   944.2   42.77  944.08   47.82  944.18   48.59  944.19    52.6  945.47
   53.74  945.75   55.26  946.12   58.69  946.65   59.79  946.88   63.17  947.19
   70.22  948.98   71.28  949.18   89.32  950.84    97.2   951.1   99.77  951.31
  100.72  951.34  105.65  951.55
#Mann= 3 , 0 , 0
       0     .07       0   30.09     .05       0   55.26     .07       0
Bank Sta=30.09,55.26
XS Rating Curve= 0 ,0
Exp/Cntr=0.3,0.1

Type RM Length L Ch R = 1 ,77      ,34.46,31.89,34.46
XS GIS Cut Line= 2
2234576.42379955 413339.82539463  2234652.419035 413285.48973487
#Sta/Elev= 21
       0  951.219.979996  951.97    24.2   951.6   29.67  950.34   33.38  949.09
   34.33  948.55   35.07  946.49   38.03  943.68   38.48  943.44   40.89  943.04
   45.09  943.22   49.15  946.62   49.89  947.12   50.53  950.35   54.08  950.68
    57.3  951.56   61.37  951.72   66.74   952.3   72.79  952.63   75.31   952.6
   93.42  952.98
#Mann= 3 , 0 , 0
       0     .07       0   35.07     .05       0   49.89     .07       0
Bank Sta=35.07,49.89
XS Rating Curve= 0 ,0
Exp/Cntr=0.3,0.1

Type RM Length L Ch R = 3 ,056.92  ,,,
Bridge Culvert--1,0,-1,-1, 0
Deck Dist Width WeirC Skew NumUp NumDn MinLoCord MaxHiCord MaxSubmerge Is_Ogee
10.7,9,2.6,0, 11, 11, , , 0.98, 0, 0,0,,
       0      36      36    49.5    49.5      60      65      68      75      80
     100
     953     954     954     954     954     954     954     954     954     954
     954
       0       0     952     952     946     946
        
       0      28      28    41.5    41.5      60      65      68      75      80
      93
     953     954     954     954     954     954     954     954     954     954
     954
       0       0     952     952     946     946
        
BR Coef=-1 , 0 , 0 ,, 0 ,,,0.8,-1,,0,
WSPro=,,,, 1 ,,,, 0 ,,,, 0 ,,,,-1 ,-1 ,-1 , 0 , 0 , 0 , 0 , 0
BC Design=,, 0 ,, 0 ,,,,,,
BC Use User HTab Curves=0
BC User HTab FreeFlow(D)= 0

Type RM Length L Ch R = 1 ,45      ,16.14,16.45,22.02
XS GIS Cut Line= 2
2234598.24487394  413356.39554292234673.80880896 413317.31074898
#Sta/Elev= 29
       0  952.83    3.75  952.774.809998  952.765.120003  952.755.169998  952.76
    22.5  951.85   26.59  946.25   28.24  943.99   29.16  942.56   29.64  942.32
   29.97  941.83   33.12  941.33   36.61  941.88   38.12  941.91   39.36  943.38
   42.55  947.15   43.78  948.12   43.79  948.13   44.91  948.48   51.56  950.59
   54.58  950.41   54.62  950.42   57.37  951.49   72.41  951.77    77.9  951.54
   80.99  951.88   81.47  951.89   83.43   952.4   85.07   952.9
#Mann= 3 , 0 , 0
       0     .07       0   26.59     .05       0   42.55     .07       0
Bank Sta=26.59,42.55
XS Rating Curve= 0 ,0
Exp/Cntr=0.3,0.1

Type RM Length L Ch R = 1 ,29      ,25.25,25.33,25.49
XS GIS Cut Line= 2
2234604.75877091 413369.914038662234681.33199988 413328.87501039
#Sta/Elev= 22
       0  947.199.899994  947.14   19.71  947.3421.82999  947.24   23.19  946.76
    24.2  946.71   26.55  946.59   28.02   944.2   29.31  941.15   38.45  941.14
   41.08  941.21   43.33  941.68   43.82  941.93   48.82  944.49   53.87  947.08
   55.39  947.37    55.7   947.3   56.82 947.701   57.18  947.83   68.39  947.88
75.68999  948.38   86.88  949.52
#Mann= 3 , 0 , 0
       0     .07       0   28.02     .05       0   48.82     .07       0
Bank Sta=28.02,48.82
XS Rating Curve= 0 ,0
Exp/Cntr=0.3,0.1

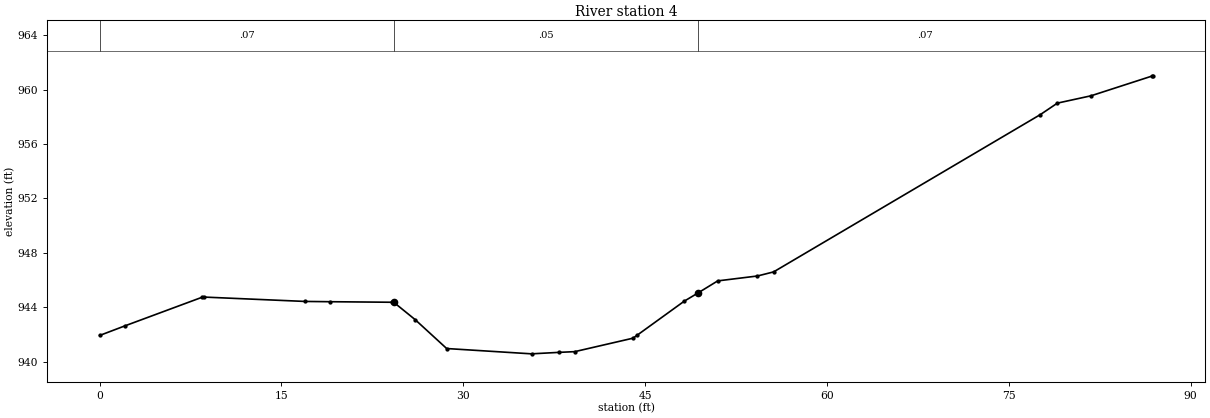
Type RM Length L Ch R = 1 ,4       ,25.54,25,25.01
XS GIS Cut Line= 2
2234616.56825371 413391.948922742234693.14148268 413350.90989447
#Sta/Elev= 25
       0  941.932.099998  942.648.459999  944.748.629997  944.75   16.95  944.43
      19  944.41   24.11  944.37   24.26  944.37   26.02   943.1   28.63  940.97
   35.63  940.58   37.93  940.69   39.19  940.74      44  941.73   44.33  941.94
   48.23  944.45   49.34  945.04   50.99  945.94   54.27   946.3    55.6   946.6
   77.61  958.1679.00999     95981.78999  959.54   86.82  960.99   86.88  961.01
#Mann= 3 , 0 , 0
       0     .07       0   24.26     .05       0   49.34     .07       0
Bank Sta=24.26,49.34
XS Rating Curve= 0 ,0
Exp/Cntr=0.3,0.1
LCMann Table=0